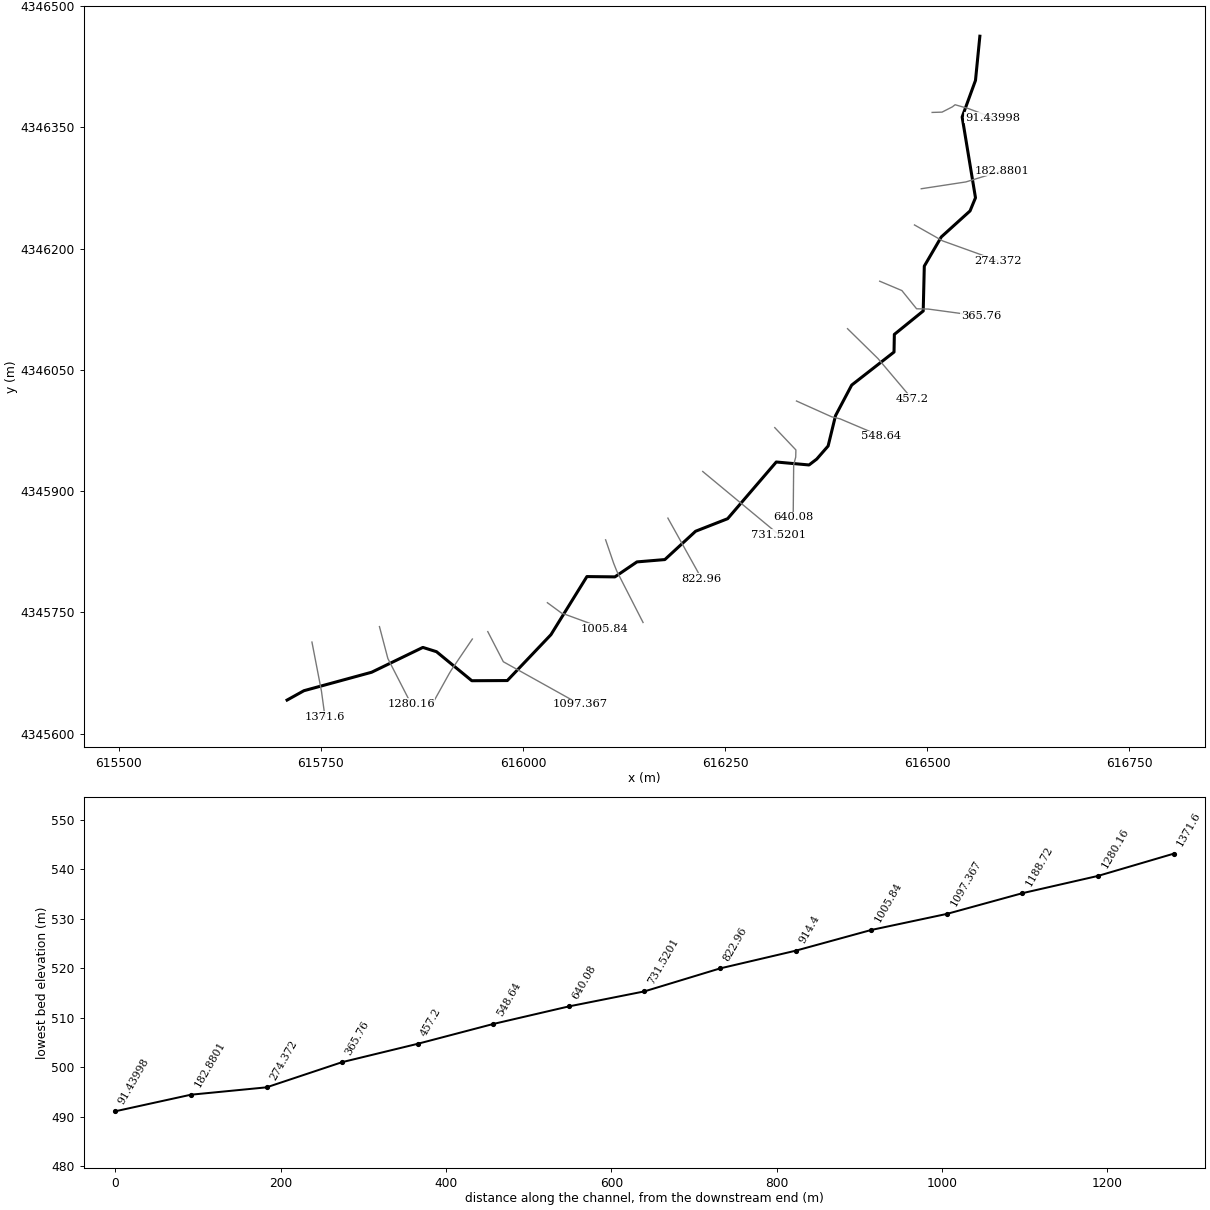
--- PantherRun.prj (project) ---

Proj Title=PantherRun
Current Plan=p01
Default Exp/Contr=0.3,0.1
SI Units
Geom File=g01
Flow File=f01
Plan File=p01
Background Map Layer=Google Hybrid
Y Axis Title=Elevation
X Axis Title(PF)=Main Channel Distance
X Axis Title(XS)=Station
BEGIN DESCRIPTION:
September 2018
Tucker County ABFE Study
US Army Corps of Engineers, Pittsburgh District
NAD 1983 UTM 17N (meters)
END DESCRIPTION:
DSS Export Rating Curves= 0
DSS Export Rating Curve Sorted= 0
DSS Export Volume Flow Curves= 0
DXF OffsetX= 0
DXF OffsetY= 0
DXF ScaleX= 1
DXF ScaleY= 10

--- PantherRun.p01 (plan) ---

Plan Title=PantherRun_plan
Program Version=5.05
Short Identifier=Plan1_subcritical
Geom File=g01
Flow File=f01
Subcritical Flow
K Sum by GR= 0
Std Step Tol= 0.003
Critical Tol= 0.003
Num of Std Step Trials= 20
Max Error Tol= 0.1
Flow Tol Ratio= 0.001
Split Flow NTrial= 30
Split Flow Tol= 0.006
Split Flow Ratio= 0.02
Log Output Level= 0
Friction Slope Method= 1
Unsteady Friction Slope Method= 2
Unsteady Bridges Friction Slope Method= 1
Parabolic Critical Depth
Global Vel Dist= 0 , 0 , 0
Global Log Level= 0
CheckData=True
Encroach Param=-1 ,0,0, 0
Computation Interval=1MIN
Output Interval=1HOUR
Instantaneous Interval=1HOUR
Mapping Interval=1HOUR
Computation Time Step Use Courant=        0
Computation Time Step Use Time Series=    0
Computation Time Step Count To Double=0
Computation Time Step Max Doubling=0
Computation Time Step Max Halving=0
Computation Time Step Residence Courant=0
Run HTab= 0
Run UNet= 0
Run Sediment= 0
Run PostProcess= 0
Run WQNet= 0
Run RASMapper=-1
UNET Theta= 1
UNET Theta Warmup= 1
UNET ZTol= 0.006
UNET ZSATol= 0.006
UNET MxIter= 20
UNET Max Iter WO Improvement= 0
UNET MaxInSteps= 0
UNET DtIC= 0
UNET DtMin= 0
UNET MaxCRTS= 20
UNET WFStab= 2
UNET SFStab= 1
UNET WFX= 1
UNET SFX= 1
UNET 1D Methodology=Finite Difference
UNET DSS MLevel= 4
UNET Pardiso=0
UNET DZMax Abort= 30
UNET Use Existing IB Tables=-1
UNET Froude Reduction=False
UNET Froude Limit= 0.8
UNET Froude Power= 4
UNET D1 Cores= 0
UNET D2 Coriolis=0
UNET D2 Cores= 0
UNET D2 Theta= 1
UNET D2 Theta Warmup= 1
UNET D2 Z Tol= 0.003
UNET D2 Volume Tol= 0.003
UNET D2 Max Iterations= 20
UNET D2 Equation= 0
UNET D2 RampUpFraction=0.1
UNET D2 TimeSlices= 1
UNET D2 BCVolumeCheck=0
UNET D1D2 MaxIter= 0
UNET D1D2 ZTol=0.003
UNET D1D2 QTol=0.1
UNET D1D2 MinQTol=0.03
Write IC File= 0
Write IC File at Fixed DateTime=0
Write IC File at Sim End=0
Echo Input=False
Echo Parameters=False
Echo Output=False
Write Detailed= 0
HDF Write Warmup=0
HDF Write Time Slices=0
HDF Flush=0
HDF Face Node Velocities=0
HDF Compression= 1
HDF Chunk Size= 1
HDF Spatial Parts= 1
HDF Use Max Rows=0
HDF Fixed Rows= 1
Calibration Method= 0
Calibration Iterations= 20
Calibration Max Change=0.05
Calibration Tolerance=0.2
Calibration Maximum=1.5
Calibration Minimum=0.5
Calibration Optimization Method= 1
WQ AD Non Conservative
WQ ULTIMATE=-1
WQ Max Comp Step=1HOUR
WQ Output Interval=15MIN
WQ Output Selected Increments= 0
WQ Output face flow=0
WQ Output face velocity=0
WQ Output face area=0
WQ Output face dispersion=0
WQ Output cell volume=0
WQ Output cell surface area=0
WQ Output cell continuity=0
WQ Output cumulative cell continuity=0
WQ Output face conc=0
WQ Output face dconc_dx=0
WQ Output face courant=0
WQ Output face peclet=0
WQ Output face adv mass=0
WQ Output face disp mass=0
WQ Output cell mass=0
WQ Output cell source sink temp=0
WQ Output nsm pathways=0
WQ Output nsm derived pathways=0
WQ Output MaxMinRange=-1
WQ Daily Max Min Mean=-1
WQ Daily Range=0
WQ Daily Time=0
WQ Create Restart=0
WQ Fixed Restart=0
WQ System Summary=0
WQ Write To DSS=0
WQ Use Fixed Temperature=0
Sorting and Armoring Iterations= 10
XS Update Threshold= 0.02
Bed Roughness Predictor= 0
Hydraulics Update Threshold= 0.02
Energy Slope Method= 1
Volume Change Method= 1
Sediment Retention Method= 0
XS Weighting Method= 0
Number of US Weighted Cross Sections= 1
Number of DS Weighted Cross Sections= 1
Upstream XS Weight=0
Main XS Weight=1
Downstream XS Weight=0
Number of DS XS's Weighted with US Boundary= 1
Upstream Boundary Weight= 1
Weight of XSs Associated with US Boundary= 0
Number of US XS's Weighted with DS Boundary= 1
Downstream Boundary Weight= 0.5
Weight of XSs Associated with DS Boundary= 0.5
Percentile Method= 0
Sediment Output Level= 4
Mass or Volume Output= 0
Output Increment Type= 1
Profile and TS Output Increment= 1
XS Output Flag= 0
XS Output Increment= 10
Write Gradation File= 0
Read Gradation Hotstart= 0
Write HDF5 File= 1
Write Binary Output= 1
Write DSS Sediment File= 0
SV Curve= 0
Specific Gage Flag= 0

--- PantherRun.f01 (steady flow) ---

Flow Title=PantherRun_flow
Program Version=5.05
Number of Profiles= 1
Profile Names=PF 1
River Rch & RM=Panther Run,1               ,1371.6
  11.866
River Rch & RM=Panther Run,1               ,1097.367
 16.0921
River Rch & RM=Panther Run,1               ,365.76
 17.0914
River Rch & RM=Panther Run,1               ,274.372
 20.4369
River Rch & RM=Panther Run,1               ,91.43998
 20.5986
Boundary for River Rch & Prof#=Panther Run,1               , 1
Up Type= 2
Dn Type= 3
Dn Slope=0.0366
DSS Import GetInterval= 0
DSS Import GetPeak= 0
DSS Import FillOption= 0

--- PantherRun.g01 (geometry) ---

Geom Title=PantherRun_geometry
Program Version=5.05

River Reach=Panther Run     ,1
Reach XY= 30
     615708.0598    4345641.4094     615728.8957    4345652.9849
     615812.7041    4345675.8458     615876.0705    4345706.5632
     615892.9377    4345701.2715      615936.641    4345665.3477
     615980.5811    4345665.5527     616034.5928    4345722.3424
     616079.0888    4345794.2301616113.7440241944345793.85442819
     616141.0014    4345812.3872     616175.5296    4345815.2645
616213.5899224354345850.32191437     616253.2287    4345865.8463
     616313.4088    4345936.0066     616353.9649    4345932.3429
616363.4617664854345939.60760435     616377.5774    4345955.7996
     616386.7298    4345993.3385      616406.747    4346031.1912
     616459.1346    4346072.0694     616459.5315    4346093.8976
     616495.2503    4346122.8695     616496.6021    4346178.4059
     616517.6365    4346214.5216     616553.1941    4346246.6948
      616559.941    4346262.9667     616543.4335    4346362.9531
      616559.941    4346408.2232      616565.353    4346462.9128

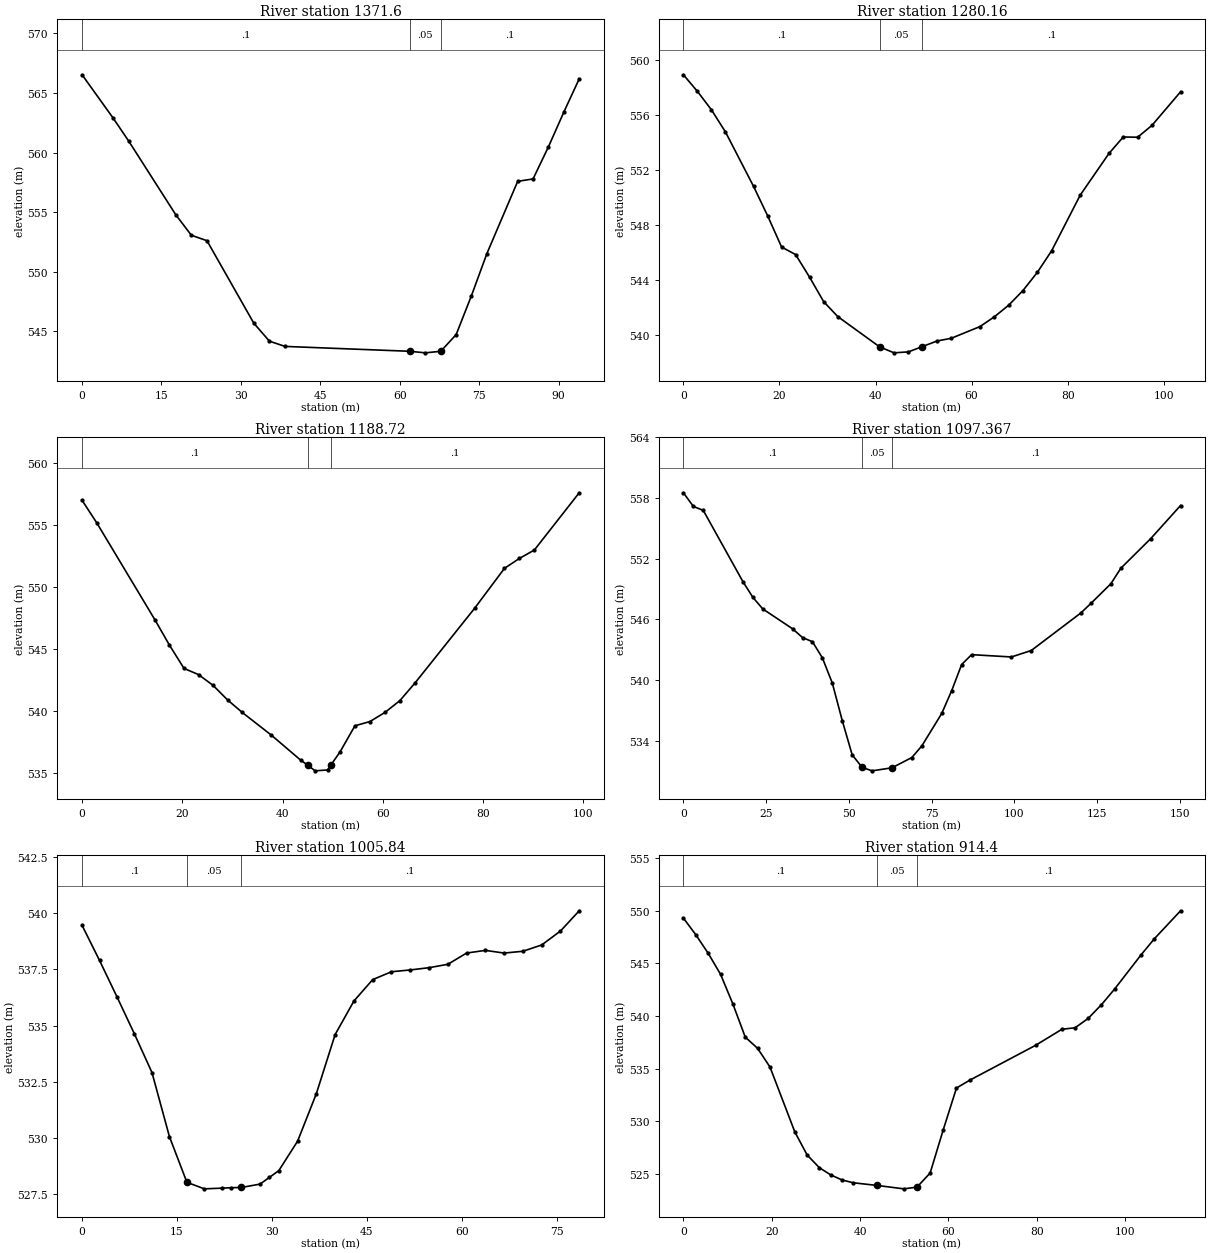
Type RM Length L Ch R = 1 ,1371.6  ,90.38,91.44,94.15
XS GIS Cut Line= 3
     615738.8256    4345713.1772     615750.6012    4345652.3729
     615754.9319     4345620.687
#Sta/Elev= 20
       0  566.53     5.9  562.87    8.85  560.93    17.7  554.77   20.64  553.05
   23.59  552.59   32.44  545.66   35.39  544.15   38.34  543.71   61.93   543.3
   64.84  543.17   67.75   543.3   70.66   544.7   73.56  547.98   76.47  551.51
   82.29  557.58   85.19  557.78    88.1  560.48   91.01   563.4   93.91  566.19
#Mann= 3 , 0 , 0
       0      .1       0   61.93     .05       0   67.75      .1       0
Bank Sta=61.93,67.75
XS Rating Curve= 0 ,0
Exp/Cntr=0.3,0.1

Type RM Length L Ch R = 1 ,1280.16 ,96.27,91.44,86.32
XS GIS Cut Line= 3
     615822.3686    4345732.3138     615832.7761    4345692.7865
     615861.3596    4345637.0486
#Sta/Elev= 29
       0  558.89    2.92  557.68    5.84  556.34    8.76  554.73    14.6  550.78
   17.52  548.65   20.44  546.37   23.36  545.82   26.28  544.17    29.2   542.4
   32.12  541.32   40.87  539.11   43.86  538.68   46.84  538.75    49.7  539.13
   52.81  539.54   55.79  539.74   61.75  540.59   64.74   541.3   67.72  542.14
    70.7  543.21   73.69  544.53   76.67   546.1   82.63  550.15    88.6  553.17
   91.58  554.37   94.57  554.35   97.55  555.21  103.51  557.65
#Mann= 3 , 0 , 0
       0      .1       0   40.87     .05       0    49.7      .1       0
Bank Sta=40.87,49.7
XS Rating Curve= 0 ,0
Exp/Cntr=0.3,0.1

Type RM Length L Ch R = 1 ,1188.72 ,82.41,91.35,104.75
XS GIS Cut Line= 4
     615937.3032     4345716.931     615911.2432    4345678.4234
     615908.6842      4345674.17     615885.5012    4345632.4548
#Sta/Elev= 26
       0  556.98    2.91  555.18   14.53  547.36   17.44  545.31   20.34  543.44
   23.25  542.94   26.15  542.07   29.06  540.89   31.97  539.89   37.78  538.06
   43.59  536.06      45  535.65    46.5  535.19   48.98  535.26   49.66  535.67
   51.46  536.71   54.44  538.82   57.43  539.16   60.41  539.89   63.39  540.84
   66.37  542.24   78.31  548.28   84.27   551.5   87.25   552.3   90.24  552.98
   99.19  557.59
#Mann= 3 , 0 , 0
       0      .1       0      45     .05       0   49.66      .1       0
Bank Sta=45,49.66
XS Rating Curve= 0 ,0
Exp/Cntr=0.3,0.1

Type RM Length L Ch R = 1 ,1097.367,90.46,91.53,92.31
XS GIS Cut Line= 3
     615956.4097    4345726.1175     615975.6613    4345688.8312
     616070.1807     4345636.159
#Sta/Elev= 30
       0  558.52       3  557.17    5.99  556.78   17.98  549.72   20.98  548.17
   23.98  547.02   32.97  545.06   35.97  544.19   38.97  543.78   41.96  542.19
   44.97  539.69   47.97  535.98   50.98  532.58   53.99  531.34   56.99     531
      63   531.3   69.01  532.32   72.02  533.47   78.03  536.68   81.04  538.94
   84.04  541.52   87.05   542.5   99.07  542.27  105.08  542.91  120.11  546.64
  123.12  547.58  129.13  549.52  132.13  551.05  141.15  553.98  150.17  557.26
#Mann= 3 , 0 , 0
       0      .1       0   53.99     .05       0      63      .1       0
Bank Sta=53.99,63
XS Rating Curve= 0 ,0
Exp/Cntr=0.3,0.1

Type RM Length L Ch R = 1 ,1005.84 ,98.44,91.44,87.63
XS GIS Cut Line= 4
     616030.1908    4345761.8649     616048.0012    4345748.8059
     616050.9336    4345747.9285     616101.0837    4345729.5889
#Sta/Elev= 30
       0  539.46    2.76   537.9    5.52  536.28    8.28  534.63   11.04  532.92
    13.8  530.07   16.56  528.04   19.32  527.75   22.09  527.78   23.52   527.8
   25.15  527.81   28.11  527.96    29.6  528.26   31.08  528.56   34.05  529.87
   37.01  531.98   39.98  534.61   42.95   536.1   45.91  537.05   48.88   537.4
   51.85  537.48   54.81  537.58   57.78  537.73   60.74  538.23   63.71  538.35
   66.68  538.23   69.64  538.31   72.61  538.59   75.58  539.21   78.54  540.11
#Mann= 3 , 0 , 0
       0      .1       0   16.56     .05       0   25.15      .1       0
Bank Sta=16.56,25.15
XS Rating Curve= 0 ,0
Exp/Cntr=0.3,0.1

Type RM Length L Ch R = 1 ,914.4   ,91.68,91.44,94.28
XS GIS Cut Line= 4
      616102.228    4345839.7039     616112.2261    4345810.5689
      616115.985    4345801.1716     616148.5637    4345737.4064
#Sta/Elev= 30
       0  549.31     2.8  547.73     5.6  545.97     8.4  543.97    11.2  541.14
      14  537.99    16.8  536.92    19.6  535.14    25.2  528.99      28  526.78
    30.8  525.56   33.33  524.89   35.86  524.41   38.39  524.14   43.91  523.88
   49.87  523.56   52.86  523.72   55.84  525.06   58.83   529.2   61.81  533.15
   64.79  533.89   79.71  537.21   85.68  538.74   88.66  538.88   91.64  539.78
   94.63  541.08   97.61  542.57  103.58  545.81  106.56  547.33  112.53  550.01
#Mann= 3 , 0 , 0
       0      .1       0   43.91     .05       0   52.86      .1       0
Bank Sta=43.91,52.86
XS Rating Curve= 0 ,0
Exp/Cntr=0.3,0.1

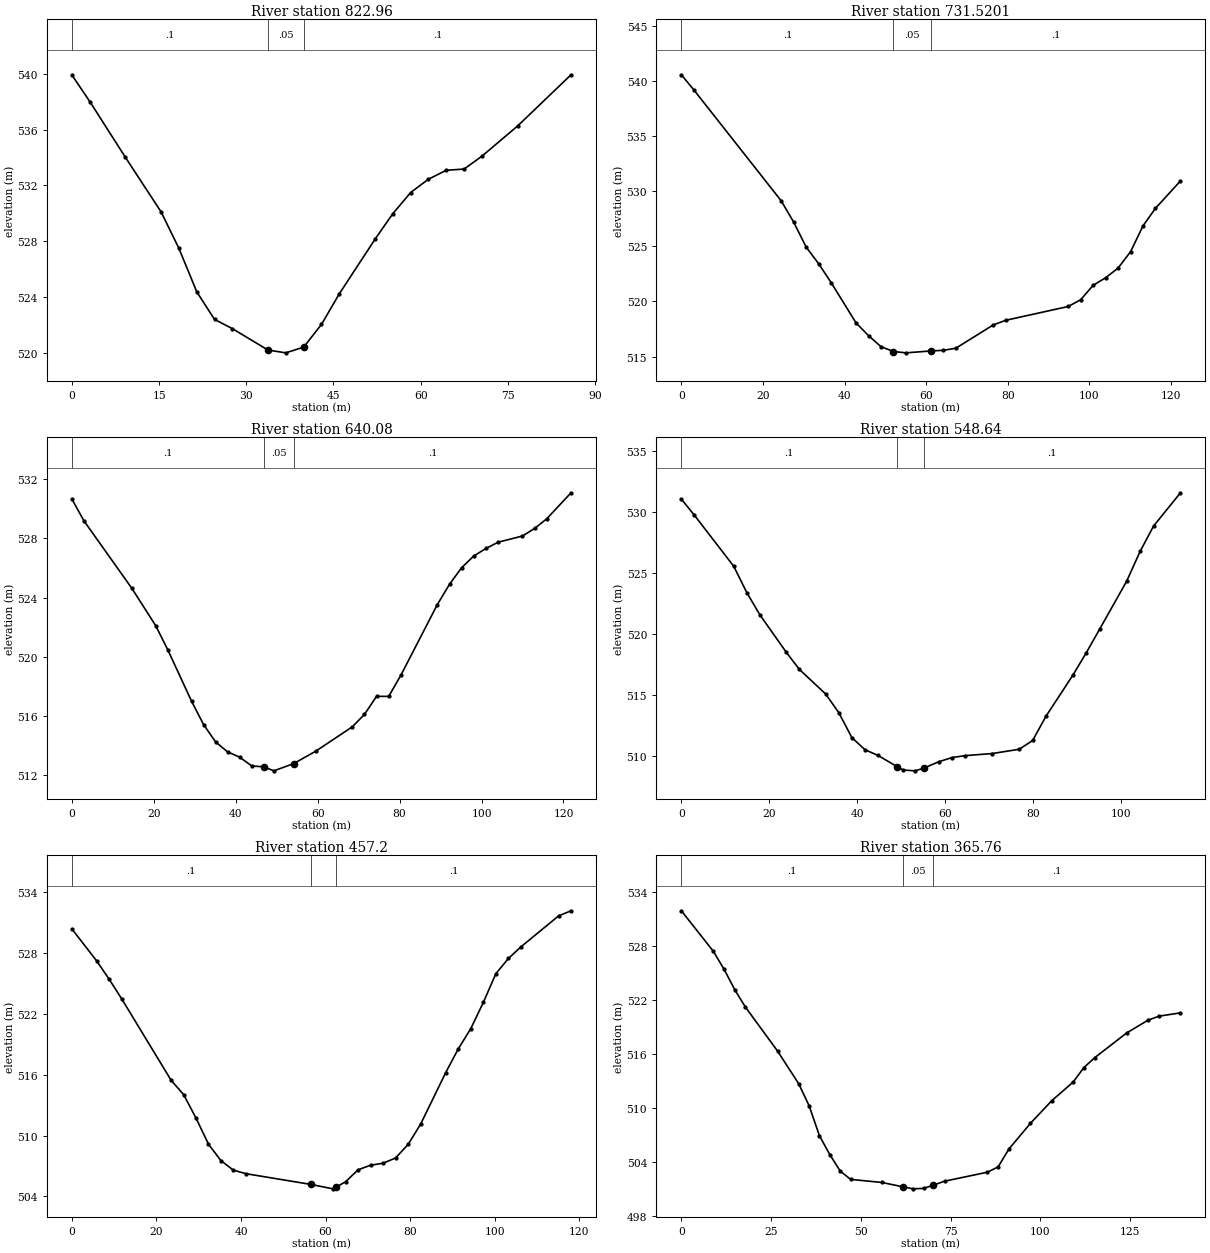
Type RM Length L Ch R = 1 ,822.96  ,90.67,91.44,98.15
XS GIS Cut Line= 2
     616179.2912    4345866.5584     616221.0822    4345791.5491
#Sta/Elev= 22
       0  539.93    3.07  538.03     9.2  534.02   15.33  530.11    18.4  527.49
   21.47  524.37   24.53  522.38    27.6  521.72   33.73  520.18    36.8  519.98
   39.87  520.39   42.93  522.02      46  524.22   52.13  528.13    55.2  529.97
   58.27  531.49   61.33  532.45    64.4  533.09   67.47  533.18   70.53   534.1
   76.67  536.27   85.87  539.95
#Mann= 3 , 0 , 0
       0      .1       0   33.73     .05       0   39.87      .1       0
Bank Sta=33.73,39.87
XS Rating Curve= 0 ,0
Exp/Cntr=0.3,0.1

Type RM Length L Ch R = 1 ,731.5201,96.99,91.44,80.41
XS GIS Cut Line= 2
     616222.4164    4345924.2548     616316.6027    4345846.1492
#Sta/Elev= 26
       0  540.54    3.06  539.17   24.47  529.12   27.53  527.19   30.59  524.93
   33.65  523.42   36.71  521.71   42.83  518.05   45.88   516.9   48.94   515.9
      52  515.46   55.06  515.34   61.18  515.51   64.24  515.57    67.3  515.76
   76.47  517.87   79.53  518.29   94.83  519.54   97.89  520.15  100.95  521.46
     104  522.14  107.06  523.02  110.12   524.5  113.18  526.85  116.24  528.44
  122.36  530.92
#Mann= 3 , 0 , 0
       0      .1       0      52     .05       0   61.18      .1       0
Bank Sta=52,61.18
XS Rating Curve= 0 ,0
Exp/Cntr=0.3,0.1

Type RM Length L Ch R = 1 ,640.08  ,69.92,91.44,113.15
XS GIS Cut Line= 5
     616311.5625     4345978.534     616337.6909    4345950.9404
     616337.4816    4345942.0727     616334.9511    4345932.7096
     616334.3457    4345867.4362
#Sta/Elev= 30
       0  530.65    2.92  529.19   14.62  524.63   20.46   522.1   23.39  520.48
   29.23  516.99   32.15  515.42   35.08  514.25      38  513.58   40.96  513.22
   43.91  512.63   46.87  512.57    49.3   512.3   54.15  512.79   59.54  513.63
   68.44  515.27   71.41  516.11   74.37  517.33   77.34  517.33   80.31  518.76
   89.21  523.53   92.18   524.9   95.14  526.02   98.11  526.81  101.08  527.32
  104.04  527.74  109.98  528.16  112.95  528.67  115.91  529.32  121.85  531.08
#Mann= 3 , 0 , 0
       0      .1       0   46.87     .05       0   54.15      .1       0
Bank Sta=46.87,54.15
XS Rating Curve= 0 ,0
Exp/Cntr=0.3,0.1

Type RM Length L Ch R = 1 ,548.64  ,94.17,91.44,85.12
XS GIS Cut Line= 4
     616338.4418    4346011.4734     616381.9546    4345991.9344
     616392.4028    4345989.3871     616443.0401    4345967.9571
#Sta/Elev= 30
       0  531.05    2.98  529.72   11.92  525.53   14.91  523.35   17.89  521.53
   23.85  518.48   26.83  517.07   32.79  515.06   35.77  513.53   38.75  511.48
   41.74  510.48   44.72  510.01   49.01   509.1   50.39  508.82   53.08  508.75
   55.12  508.97   58.45  509.49   61.51  509.84   64.56     510   70.67  510.17
   76.78  510.52   79.84  511.24   82.89  513.24      89  516.61   92.05  518.45
   95.11   520.4  101.22  524.32  104.27  526.76  107.33  528.84  113.44  531.57
#Mann= 3 , 0 , 0
       0      .1       0   49.01     .05       0   55.12      .1       0
Bank Sta=49.01,55.12
XS Rating Curve= 0 ,0
Exp/Cntr=0.3,0.1

Type RM Length L Ch R = 1 ,457.2   ,80.26,91.44,94.05
XS GIS Cut Line= 3
     616401.5835    4346100.9826     616439.3106    4346063.9611
     616481.4394    4346014.1784
#Sta/Elev= 30
       0  530.39    5.87  527.23    8.81  525.43   11.75  523.51   23.49  515.44
   26.43  514.04   29.37  511.71    32.3  509.15   35.24  507.53   38.17  506.59
   41.11  506.24   56.47  505.18   61.75  504.74   62.47  504.91   64.72  505.43
   67.68  506.62   70.64  507.07   73.61  507.27   76.57  507.79   79.54  509.13
    82.5  511.14   88.43  516.22   91.39  518.55   94.36  520.56   97.32  523.14
  100.29  525.98  103.25  527.48  106.22  528.63  115.11  531.68  118.07  532.19
#Mann= 3 , 0 , 0
       0      .1       0   56.47     .05       0   62.47      .1       0
Bank Sta=56.47,62.47
XS Rating Curve= 0 ,0
Exp/Cntr=0.3,0.1

Type RM Length L Ch R = 1 ,365.76  ,93.59,91.39,86.26
XS GIS Cut Line= 5
      616441.399    4346159.7423     616468.8496    4346148.1668
      616487.038    4346125.6086     616501.5976    4346125.2542
     616566.7456    4346116.4167
#Sta/Elev= 30
       0  531.95    8.94  527.43   11.92  525.43    14.9  523.16   17.87  521.23
   26.81  516.35   32.69  512.72   35.59  510.28   38.48  506.93   41.38  504.83
   44.28     503   47.18  502.08   55.87  501.74   61.68  501.26   64.59  501.03
   67.51  501.08   70.05  501.41   73.33  501.88   85.29  502.88   88.27  503.47
   91.26  505.45   97.24   508.3  103.22  510.83  109.19  512.91  112.18  514.52
  115.17  515.61  124.14  518.38  130.11   519.8   133.1  520.23  139.08   520.6
#Mann= 3 , 0 , 0
       0      .1       0   61.68     .05       0   70.05      .1       0
Bank Sta=61.68,70.05
XS Rating Curve= 0 ,0
Exp/Cntr=0.3,0.1

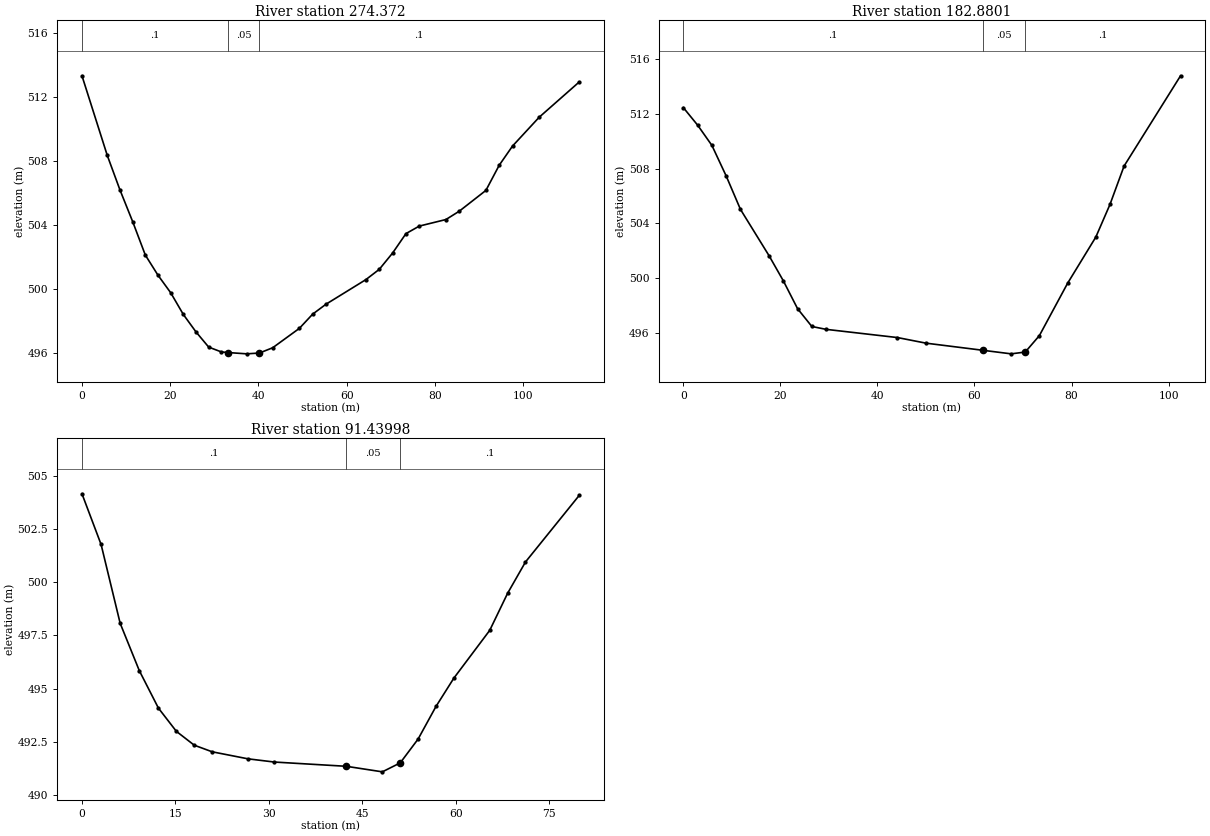
Type RM Length L Ch R = 1 ,274.372 ,78.42,91.49,95.44
XS GIS Cut Line= 3
     616484.4412    4346229.3585     616519.4385    4346209.5733
     616587.6289    4346185.0407
#Sta/Elev= 30
       0  513.31    5.74  508.33    8.61  506.18   11.49   504.2   14.36  502.11
   17.23  500.85    20.1  499.76   22.97   498.4   25.84  497.31   28.72  496.36
   31.59  496.06   33.15  496.02   37.33  495.94    40.2  495.99   43.22  496.32
   49.26  497.53   52.28  498.42    55.3  499.04   64.36  500.58   67.38  501.22
    70.4  502.24   73.42  503.45   76.44  503.92   82.48  504.33    85.5  504.85
   91.54  506.15   94.55  507.72   97.57  508.92  103.61  510.72  112.67  512.92
#Mann= 3 , 0 , 0
       0      .1       0   33.15     .05       0    40.2      .1       0
Bank Sta=33.15,40.2
XS Rating Curve= 0 ,0
Exp/Cntr=0.3,0.1

Type RM Length L Ch R = 1 ,182.8801,94.01,91.44,88.47
XS GIS Cut Line= 3
     616492.8197    4346274.1393     616548.0801     4346282.593
     616592.5902    4346296.2886
#Sta/Elev= 21
       0  512.45    2.94  511.17    5.88  509.69    8.83  507.45   11.77  505.01
   17.65  501.63    20.6  499.79   23.54  497.75   26.48  496.45   29.42  496.24
   44.13  495.64   50.02  495.23   61.72  494.71   67.55  494.45   70.46  494.58
   73.37  495.78   79.19  499.61   85.01  502.99   87.92  505.37   90.83  508.18
  102.47  514.78
#Mann= 3 , 0 , 0
       0      .1       0   61.72     .05       0   70.46      .1       0
Bank Sta=61.72,70.46
XS Rating Curve= 0 ,0
Exp/Cntr=0.3,0.1

Type RM Length L Ch R = 1 ,91.43998,100.73,91.44,88.67
XS GIS Cut Line= 6
     616506.3135    4346368.5957      616518.577    4346368.9642
     616531.3829    4346375.5155     616534.6867    4346378.1208
     616551.3442    4346373.3192     616580.9261    4346362.2457
#Sta/Elev= 20
       0  504.15    3.07  501.77    6.13  498.07     9.2  495.85   12.27  494.09
   15.15     493   18.02  492.35    20.9  492.04   26.65  491.71   30.86  491.56
   42.42  491.36    48.2   491.1   51.07  491.52   53.94  492.64   56.81  494.17
   59.68   495.5   65.43  497.74    68.3  499.48   71.17  500.95   79.78  504.07
#Mann= 3 , 0 , 0
       0      .1       0   42.42     .05       0   51.07      .1       0
Bank Sta=42.42,51.07
XS Rating Curve= 0 ,0
Exp/Cntr=0.3,0.1
LCMann Table=0

Chan Stop Cuts=-1
Use User Specified Reach Order=0
Composite Channel Slope=5